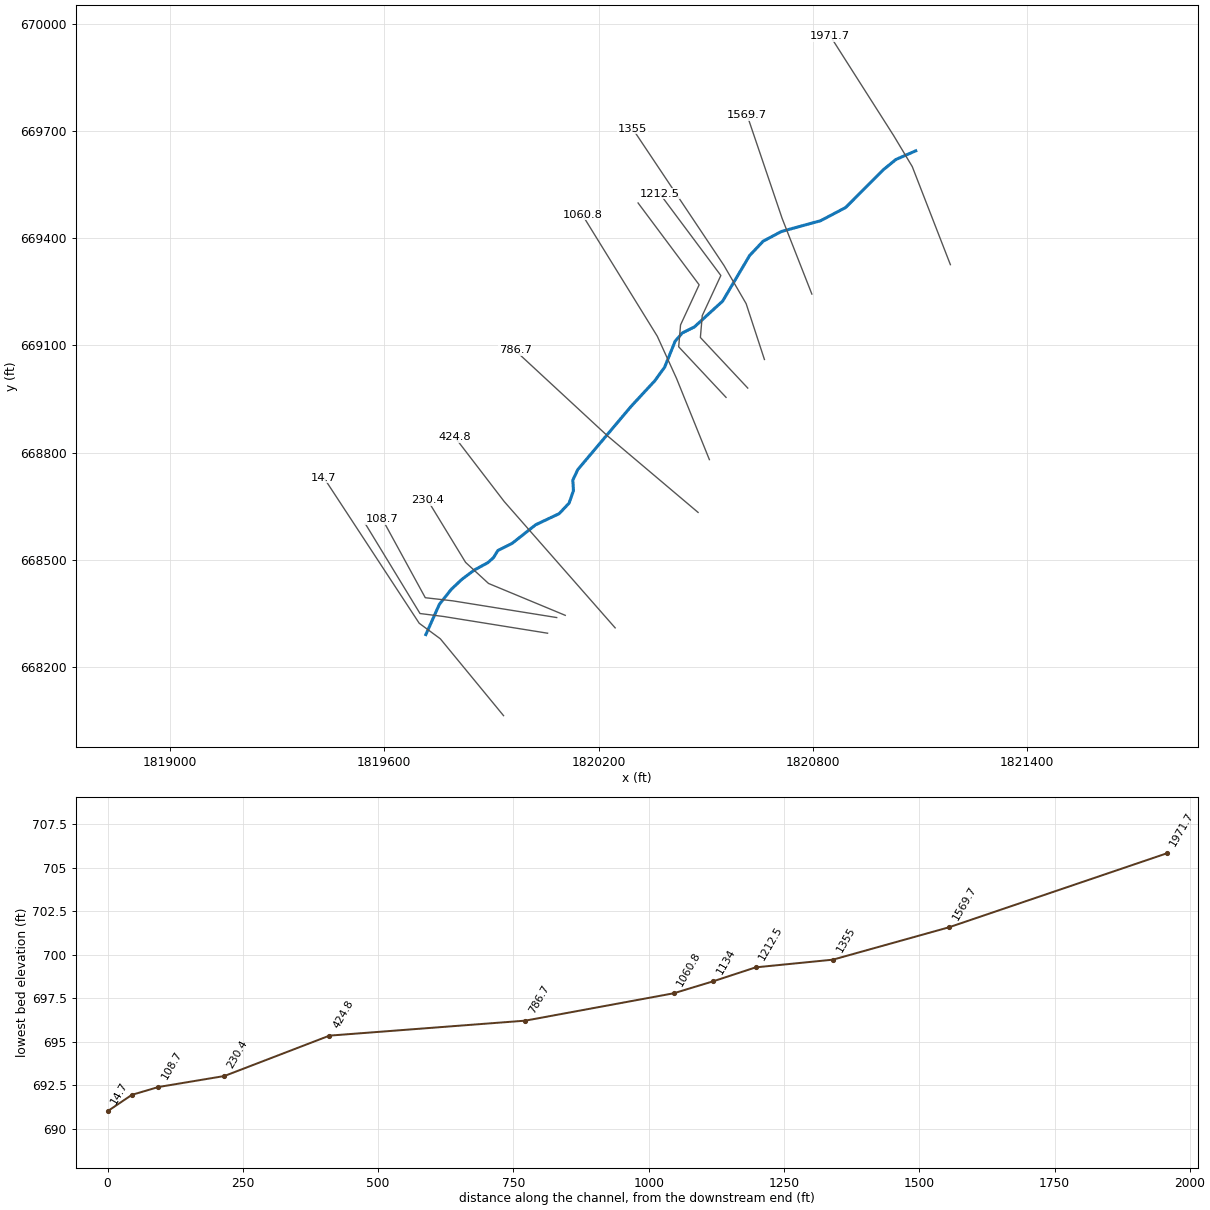
--- BuffaloCrk.prj (project) ---

Proj Title=BuffaloCrk
Current Plan=p01
Default Exp/Contr=0,0
English Units
Geom File=g01
Flow File=f01
Plan File=p01
BEGIN DESCRIPTION:
AMEC Environment & Infrastructure, 2013
Projection: NAD 1983 State Plane West Virginia South FIPS 4702 (US Feet)
Vertical Datum: NAVD 1988
END DESCRIPTION:
DSS Export Rating Curves= 0
DSS Export Rating Curve Sorted= 0
DSS Export Volume Flow Curves= 0
DXF OffsetX= 0
DXF OffsetY= 0
DXF ScaleX= 0
DXF ScaleY= 0

--- BuffaloCrk.p01 (plan) ---

Plan Title=Floodplain
Program Version=4.00
Geom File=g01
Flow File=f01
K Sum by GR=0
Std Step Tol=0.01
Critical Tol=0.01
Num of Std Step Trials=20
Max Error Tol=0.3
Flow Tol Ratio=0.001
Split Flow NTrial=30
Split Flow Tol=0.02
Split Flow Ratio=0.02
Log Output Level=0
Friction Slope Method=1
Unsteady Friction Slope Method=2
Unsteady Bridges Friction Slope Method=1
Global Log Level=0
CheckData=False
Run HTab=0
Run UNet=0
Run PostProcess=0
UNET Theta=0
UNET Theta Warmup=0
UNET ZTol=0
UNET ZSATol=0
UNET MxIter=0
UNET MaxInSteps=0
UNET DtIC=0
UNET DtMin=0
UNET MaxCRTS=0
UNET WFStab=0
UNET SFStab=0
UNET WFX=0
UNET SFX=0
UNET DSS MLevel=0
UNET DZMax Abort=0
UNET Convert EG Bridges=0
UNET Use Existing IB Tables=0
UNET Froude Limit=0
UNET Froude Power=0
Write IC File=0
Echo Input=False
Echo Output=False
Write Detailed=0

--- BuffaloCrk.f01 (steady flow) ---

Flow Title=NFF Regression Equation
Program Version=4.10
Number of Profiles= 1
Profile Names=P100yr
River Rch & RM=BuffaloCrk,Main            ,1971.7
821.5581
River Rch & RM=BuffaloCrk,Main            ,1569.7
1024.549
River Rch & RM=BuffaloCrk,Main            ,230.4
1071.559
Boundary for River Rch & Prof#=BuffaloCrk,Main            , 1
Up Type= 0
Dn Type= 3
Dn Slope=0.00918
DSS Import GetInterval= 0
DSS Import GetPeak= 0
DSS Import FillOption= 0

--- BuffaloCrk.g01 (geometry) ---

Geom Title=USGS 3m DEM
Program Version=4.10

River Reach=BuffaloCrk      ,Main
Reach XY= 30
     1821088.343      669644.965     1821032.769      669620.646
     1820998.374      669592.696     1820892.186      669486.284
     1820822.015      669449.249     1820712.064       669419.01
     1820661.066      669391.883     1820623.088      669351.736
     1820547.548      669224.091     1820468.364      669151.679
     1820434.372       669134.68     1820414.528       669111.73
     1820385.009      669038.784     1820357.225      669000.573
     1820291.234      668929.362     1820141.888      668752.202
     1820127.997      668722.676     1820129.736      668693.151
     1820117.581      668658.415     1820089.796      668628.889
     1820023.802      668597.622      1819957.81      668545.514
        1819918.      668525.605     1819905.711      668505.565
     1819890.081      668491.669     1819851.875      668470.826
     1819817.142      668444.771      1819787.62      668416.981
     1819754.098      668374.622     1819716.423      668290.193

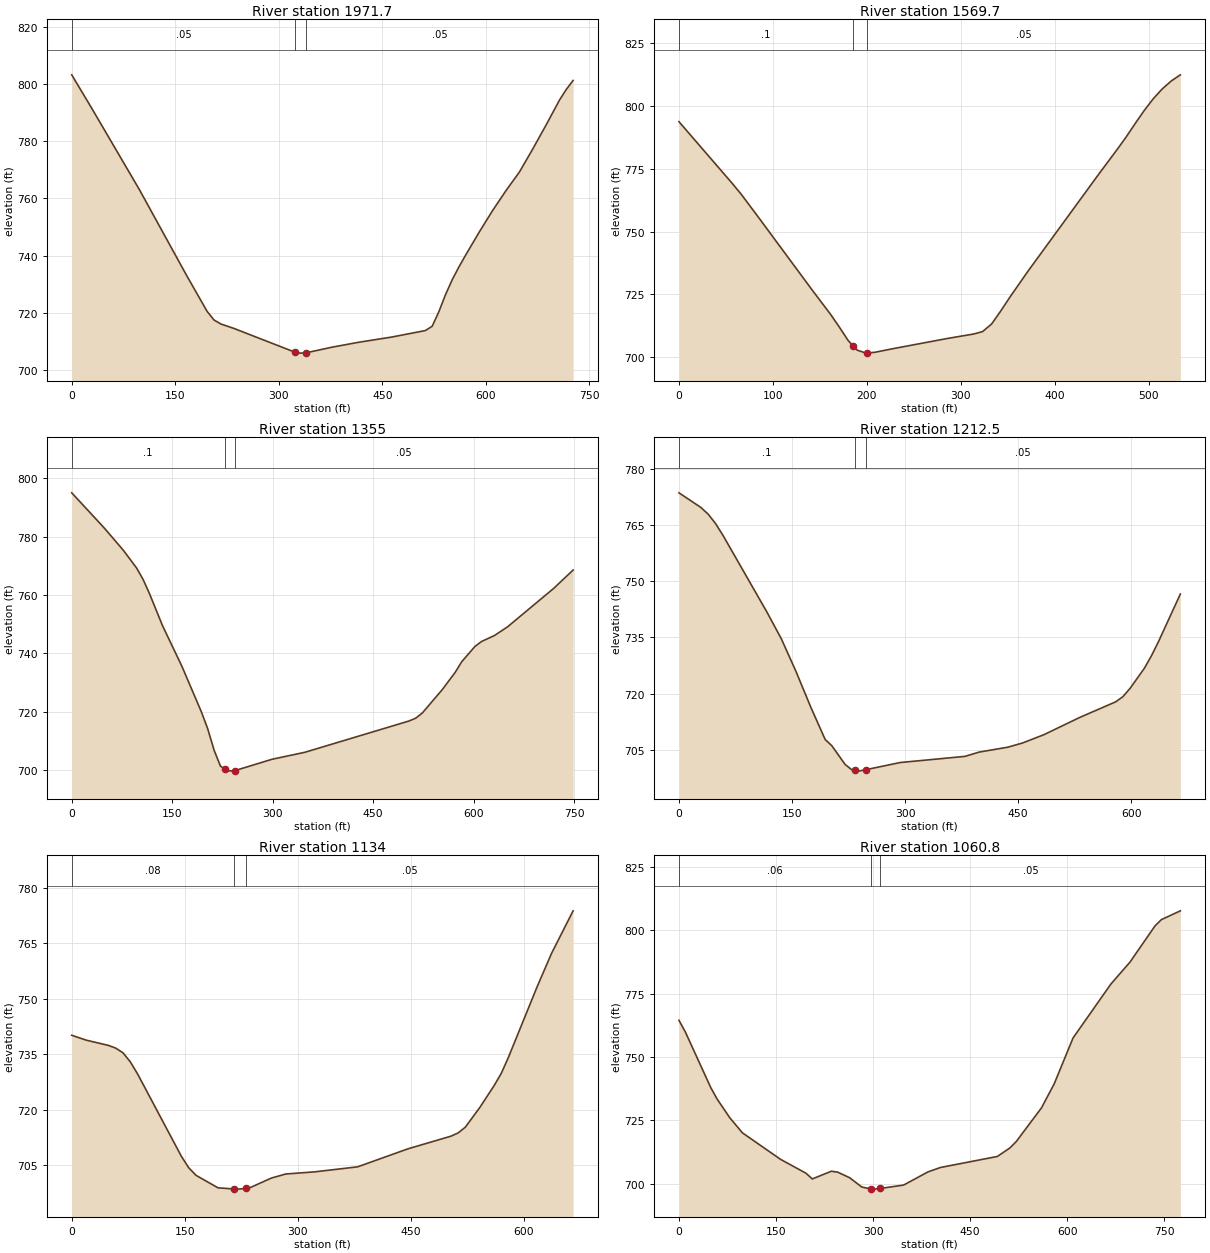
Type RM Length L Ch R = 1 ,1971.7  ,405.6,402,398.1
XS GIS Cut Line= 4
     1821185.313      669326.172       1821078.6      669600.651
     1821026.517      669687.456     1820848.942      669966.363
#Sta/Elev= 30
       0  803.33    29.4  791.45    98.2  763.03   166.9  732.84   196.3  720.39
   206.2  717.42     216  716.04   235.6  714.42     324  706.09   331.3  705.82
     339   705.9   377.3  707.91   415.2   709.6   463.8  711.46   512.4  713.73
   522.2  715.23   531.9  720.31   541.6  726.34   551.3  731.55     561  736.04
   570.8  740.19   590.2  748.16   609.7  755.75   629.1  762.74   648.6  769.26
     668  777.37   687.5  785.85   706.9  794.58   716.6  798.24   726.4  801.36
#Mann= 3 , 0 , 0
       0     .05       0     324     .04       0     339     .05       0
Bank Sta=324,339
XS Rating Curve= 0 ,0
Exp/Cntr=0.3,0.1

Type RM Length L Ch R = 1 ,1569.7  ,213.3,214.7,218.1
XS GIS Cut Line= 3
     1820797.381      669243.754      1820714.19      669455.554
     1820615.869      669745.442
#Sta/Elev= 30
       0  793.77    56.9  769.11    66.4   764.8    85.3  755.34   142.2  726.51
   161.2  717.12   170.7  711.95   180.2  706.55   185.6  704.39   189.6  702.79
   199.1  701.58   200.6  701.63   208.6  701.92   227.6  703.34     285  707.37
   313.6  709.19   323.2  710.16   332.8  713.19   342.3  718.24   351.9  723.67
     371  733.95   447.6  773.26   466.7  782.83   476.3  787.83   485.8  793.13
   495.4   798.3     505  802.97   514.5  806.85   524.1  810.01   533.7  812.44
#Mann= 3 , 0 , 0
       0      .1       0   185.6    .045       0   200.6     .05       0
Bank Sta=185.6,200.6
XS Rating Curve= 0 ,0
Exp/Cntr=0.3,0.1

Type RM Length L Ch R = 1 ,1355    ,158.4,142.5,103.1
XS GIS Cut Line= 4
     1820664.568      669060.594     1820613.323       669216.97
     1820550.823      669324.609     1820295.614      669706.554
#Sta/Elev= 30
       0     795    48.4     783    77.4  775.23    96.8  769.27   106.5  765.36
   116.2  760.42   135.5  749.53   164.6  735.55   193.3  720.13   202.9  714.29
   212.4  706.96     222  701.43   228.1  700.48   231.6  699.94   241.2  699.72
   243.1  699.86   298.8  703.77   347.7  706.15     504  716.92   513.8  717.89
   523.6  719.69   552.9  727.57   572.5  733.57   582.2   737.2   601.8  742.38
   611.6  744.09   631.1  746.16   650.6  749.13   719.1  762.22   748.4  768.56
#Mann= 3 , 0 , 0
       0      .1       0   228.1    .045       0   243.1     .05       0
Bank Sta=228.1,243.1
XS Rating Curve= 0 ,0
Exp/Cntr=0.3,0.1

Type RM Length L Ch R = 1 ,1212.5  ,76.4,78.5,96.8
XS GIS Cut Line= 5
     1820617.861      668980.539     1820485.227      669122.179
     1820490.435      669183.377     1820542.518       669295.79
     1820371.511      669524.956
#Sta/Elev= 30
       0  773.66    29.1  769.75    38.8  767.94    48.5  765.46    58.2  762.36
   116.4   741.9   135.8  734.66   155.2  725.96   174.6  716.52     194  707.73
   202.8  706.08   220.4  701.08   229.1  699.68   233.4  699.48   237.9  699.28
   248.4  699.68   293.6  701.58   379.4  703.22   398.4  704.37   436.5  705.68
   455.6  706.78   484.2  709.01   531.9  713.64   579.5   717.8     589  719.17
   598.6   721.4   617.6  726.78   627.2   730.2   636.7  734.06   665.3  746.61
#Mann= 3 , 0 , 0
       0      .1       0   233.4    .045       0   248.4     .05       0
Bank Sta=233.4,248.4
XS Rating Curve= 0 ,0
Exp/Cntr=0.3,0.1

Type RM Length L Ch R = 1 ,1134    ,61.8,73.2,86.2
XS GIS Cut Line= 5
     1820557.097      668954.497     1820424.463      669096.137
     1820429.671      669157.335     1820481.754      669269.748
     1820310.747      669498.915
#Sta/Elev= 30
       0  740.11    19.4  738.78    48.5  737.38    58.2  736.65    67.9  735.38
    77.6  732.96    87.3  729.68   145.5  707.36   155.2  704.28   164.9  702.22
     194  698.84   215.7  698.51   220.4  698.48   230.7  698.65   237.9  698.99
     265  701.48     284  702.57   322.2  703.15   379.4  704.51   446.1  709.38
   503.3  712.81   512.8  713.69   522.3  715.25   541.4  720.54   560.4  726.46
     570  729.81   579.5  734.15   617.6  753.25   636.7  762.27   665.3  773.78
#Mann= 3 , 0 , 0
       0     .08       0   215.7    .045       0   230.7     .05       0
Bank Sta=215.7,230.7
XS Rating Curve= 0 ,0
Exp/Cntr=0.3,0.1

Type RM Length L Ch R = 1 ,1060.8  ,260.1,274.1,287.4
XS GIS Cut Line= 4
       1820510.4      668780.165     1820418.386      669007.595
     1820364.567      669125.651     1820154.497      669465.929
#Sta/Elev= 30
       0  764.41     9.8  759.85    49.1  737.89    58.9  733.37    78.5  725.98
    98.1     720     157  709.55   196.3  704.07   206.1  701.81   235.5  704.86
   245.3   704.5   263.9  702.28   282.4  698.65   296.2  697.85   300.9  697.79
   311.2  698.05   347.3   699.4   384.8  704.58   404.3  706.34   492.1  710.68
   511.6  714.06   521.4  716.58   560.4  729.88   579.9  739.29   609.2  757.48
   667.7  778.76     697  787.34     736  801.74   745.7  804.16     775  807.64
#Mann= 3 , 0 , 0
       0     .06       0   296.2    .045       0   311.2     .05       0
Bank Sta=296.2,311.2
XS Rating Curve= 0 ,0
Exp/Cntr=0.3,0.1

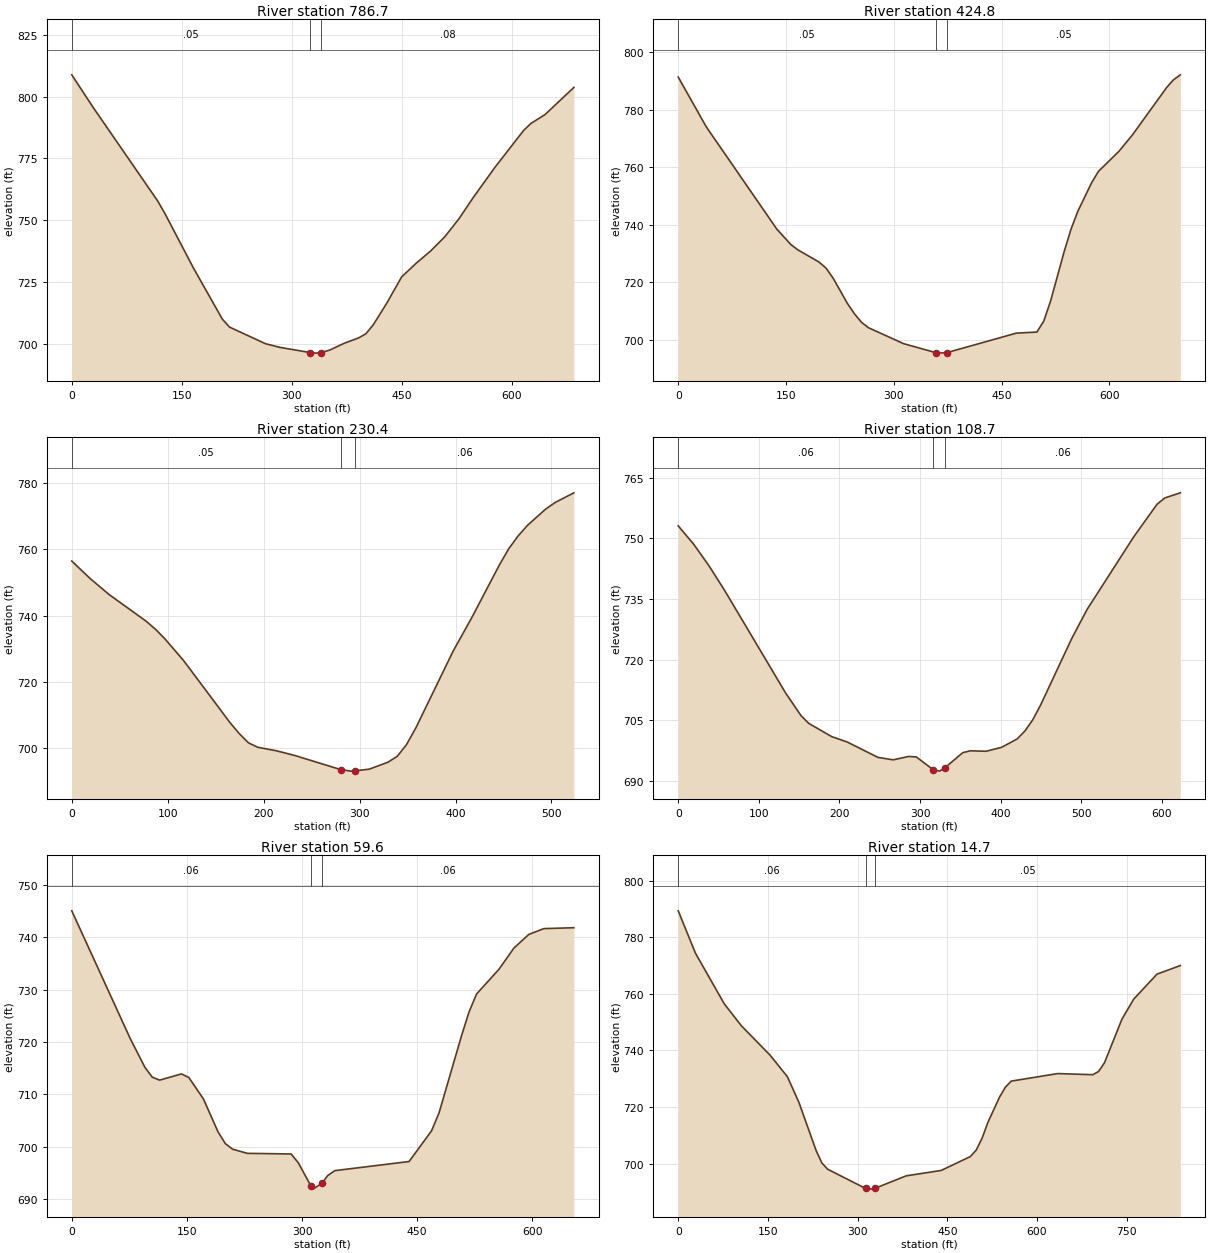
Type RM Length L Ch R = 1 ,786.7   ,365.3,361.9,359.5
XS GIS Cut Line= 3
     1820478.774      668632.335      1820225.01      668846.753
     1819966.621      669085.894
#Sta/Elev= 30
       0  808.78    29.3  795.53   117.2  757.72     127  752.66   166.1   730.5
   205.2  709.98     215  706.75   263.8  700.06   283.4  698.56   324.7  696.47
   332.2  696.22   339.7   696.4   351.8  697.48   371.3   700.2   390.9  702.37
   400.7  704.01   410.5   707.5   420.2  712.05     430  716.77   449.6  727.04
   469.1   732.5   488.7  737.42   508.3  743.25   527.8  750.59   547.4  759.24
   576.7  771.34   615.8  786.26   625.6  789.07   645.2  792.74   684.3  803.68
#Mann= 3 , 0 , 0
       0     .05       0   324.7    .045       0   339.7     .08       0
Bank Sta=324.7,339.7
XS Rating Curve= 0 ,0
Exp/Cntr=0.3,0.1

Type RM Length L Ch R = 1 ,424.8   ,191,194.4,196.6
XS GIS Cut Line= 3
     1820246.569      668308.984     1819935.935      668662.678
     1819797.127      668843.683
#Sta/Elev= 30
       0  791.34    39.2  773.97   137.3  738.46   156.9  733.08   166.7  731.24
   196.1  727.01     206  724.85   215.8  721.33   235.4  712.67   245.2  709.06
     255   706.1   264.8  704.19   313.8  698.64   358.7  695.52   362.9  695.36
   373.7  695.52   470.7  702.32   499.2  702.68   508.8  706.51   518.3  713.52
   537.3  730.78   546.8  738.54   556.3  744.74   575.3  754.58   584.8  758.54
   613.3  765.51   632.3  771.28   679.8  787.73   689.3  790.39   698.8  792.13
#Mann= 3 , 0 , 0
       0     .05       0   358.7    .045       0   373.7     .05       0
Bank Sta=358.7,373.7
XS Rating Curve= 0 ,0
Exp/Cntr=0.3,0.1

Type RM Length L Ch R = 1 ,230.4   ,105.6,121.7,136.6
XS GIS Cut Line= 4
     1820106.808      668344.103     1819891.911      668433.377
     1819827.675      668492.404     1819721.772      668666.015
#Sta/Elev= 30
       0  756.43    19.4  751.09    38.8  746.35    77.6  738.26    87.3  735.84
      97  732.98   116.4  726.46   164.8  707.72   174.5  704.38   184.2  701.57
   193.9  700.24   213.3  699.18   232.7  697.74   280.1  693.52   290.9  693.04
   295.1  693.12   310.2  693.64   329.6  695.74   339.3  697.52     349  701.08
   358.7  706.13   397.4   729.2   416.8   739.3   445.8  755.31   455.5  760.17
   465.2     764   474.9  767.18   494.2  772.18   503.9  774.11   523.3  777.02
#Mann= 3 , 0 , 0
       0     .05       0   280.1    .045       0   295.1     .06       0
Bank Sta=280.1,295.1
XS Rating Curve= 0 ,0
Exp/Cntr=0.3,0.1

Type RM Length L Ch R = 1 ,108.7   ,51.3,49.1,48.2
XS GIS Cut Line= 4
     1820082.883       668337.89     1819791.216      668384.765
     1819714.827      668393.446     1819594.602      668613.498
#Sta/Elev= 30
       0  753.04    19.1  748.54    38.1  743.19    57.2  737.21   133.4  711.68
   152.5  706.09     162  704.21   190.6  700.93   209.6  699.62   247.8  695.81
   266.8   695.2   285.9  696.04   295.4  695.92   316.1   692.8   324.2  692.41
   331.1  693.27   353.1  696.98   362.7  697.44   381.9  697.32   401.2  698.29
   420.5  700.36   430.2  702.34   439.8  705.07   449.4  708.65     488  725.08
   507.3  732.38   565.2  750.34   594.1  758.39   603.8  759.96     623  761.22
#Mann= 3 , 0 , 0
       0     .06       0   316.1    .045       0   331.1     .06       0
Bank Sta=316.1,331.1
XS Rating Curve= 0 ,0
Exp/Cntr=0.3,0.1

Type RM Length L Ch R = 1 ,59.6    ,56.5,44.9,33.3
XS GIS Cut Line= 4
     1820057.275      668294.054     1819765.609      668340.929
      1819700.07      668349.175     1819547.727      668599.175
#Sta/Elev= 30
       0     745    76.2  720.65    95.3  715.18   104.8  713.31   114.4  712.73
   142.9  713.92   152.5  713.24   171.5  709.16   190.6  702.87   200.1  700.63
   209.6  699.57   228.7  698.78   285.9  698.66   295.4  696.93   311.4  692.62
   314.3  691.96   326.4   693.1   333.2  694.51   342.6  695.48   439.5  697.22
   468.8  703.07   478.6  706.51   507.8  721.16   517.6   725.7   527.4  729.14
   556.6  733.85   576.2  737.92   595.7  740.52   615.2  741.61   654.2  741.78
#Mann= 3 , 0 , 0
       0     .06       0   311.4    .045       0   326.4     .06       0
Bank Sta=311.4,326.4
XS Rating Curve= 0 ,0
Exp/Cntr=0.3,0.1

Type RM Length L Ch R = 1 ,14.7    ,10.9,14.7,18.6
XS GIS Cut Line= 4
     1819934.011      668063.151     1819756.928      668278.429
       1819697.9      668321.831     1819430.539      668729.817
#Sta/Elev= 30
       0  789.33    28.8  774.37    76.9  756.51   105.7   748.7   153.8   738.3
   182.6  730.73   201.9  721.65   230.7  704.61   240.3  700.25   249.9  698.05
   313.4  691.26   324.5  691.02   328.4  691.25   381.3  695.71   439.8  697.62
   488.6  702.52   498.4  704.79   508.1  708.94   517.9  714.56   537.4  723.52
   547.1  726.98   556.9  729.17   634.9  731.84   693.5  731.44   703.2   732.6
     713  735.67   742.2  751.07   761.8  758.11   800.8  766.97   839.8  769.99
#Mann= 3 , 0 , 0
       0     .06       0   313.4    .045       0   328.4     .05       0
Bank Sta=313.4,328.4
XS Rating Curve= 0 ,0
Exp/Cntr=0.3,0.1

Chan Stop Cuts=-1
Use User Specified Reach Order=0
Composite Channel Slope=5